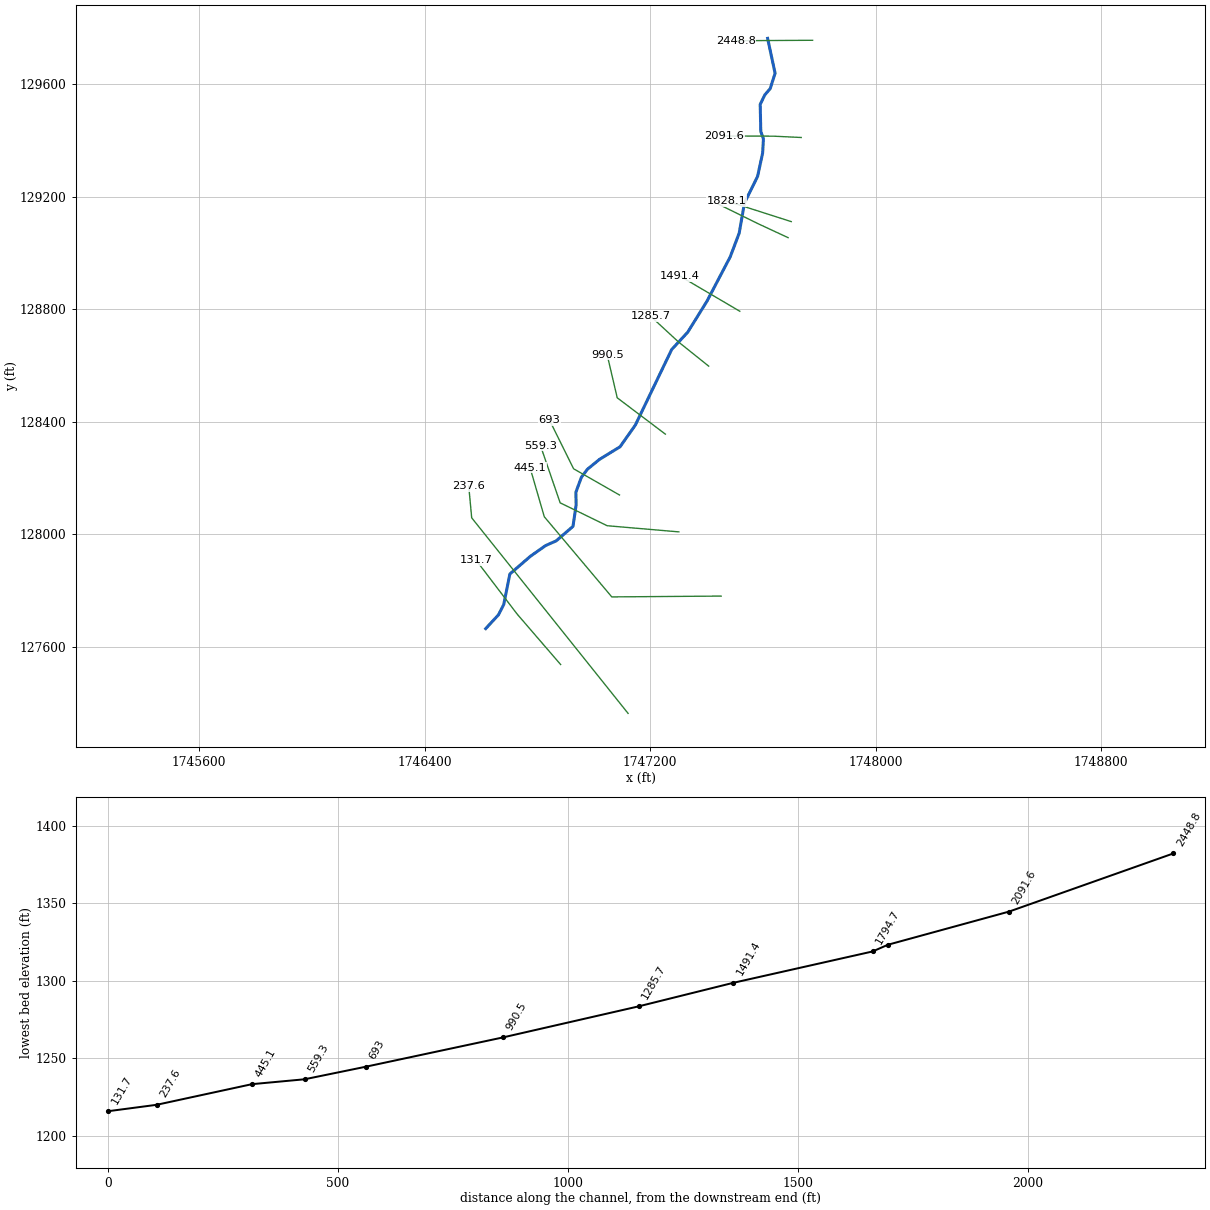
--- Atwell Branch.prj (project) ---

Proj Title=Atwell Branch
Current Plan=p01
Default Exp/Contr=0,0
English Units
Geom File=g01
Flow File=f01
Plan File=p01
BEGIN DESCRIPTION:
END DESCRIPTION:
DSS Export Rating Curves= 0
DSS Export Rating Curve Sorted= 0
DSS Export Volume Flow Curves= 0
DXF OffsetX= 0
DXF OffsetY= 0
DXF ScaleX= 0
DXF ScaleY= 0

--- Atwell Branch.p01 (plan) ---

Plan Title=Floodplain
Program Version=4.00
Geom File=g01
Flow File=f01
K Sum by GR=0
Std Step Tol=0.01
Critical Tol=0.01
Num of Std Step Trials=20
Max Error Tol=0.3
Flow Tol Ratio=0.001
Split Flow NTrial=30
Split Flow Tol=0.02
Split Flow Ratio=0.02
Log Output Level=0
Friction Slope Method=1
Unsteady Friction Slope Method=2
Unsteady Bridges Friction Slope Method=1
Global Log Level=0
CheckData=False
Run HTab=0
Run UNet=0
Run PostProcess=0
UNET Theta=0
UNET Theta Warmup=0
UNET ZTol=0
UNET ZSATol=0
UNET MxIter=0
UNET MaxInSteps=0
UNET DtIC=0
UNET DtMin=0
UNET MaxCRTS=0
UNET WFStab=0
UNET SFStab=0
UNET WFX=0
UNET SFX=0
UNET DSS MLevel=0
UNET DZMax Abort=0
UNET Convert EG Bridges=0
UNET Use Existing IB Tables=0
UNET Froude Limit=0
UNET Froude Power=0
Write IC File=0
Echo Input=False
Echo Output=False
Write Detailed=0

--- Atwell Branch.f01 (steady flow) ---

Flow Title=NFF Regression Equation
Program Version=4.00
Number of Profiles=1
Profile Names=P100yr
River Rch & RM=Atwell Branch,Main      ,2448.8
558.6881
River Rch & RM=Atwell Branch,Main      ,2091.6
565.1553
River Rch & RM=Atwell Branch,Main      ,1794.7
637.6247
River Rch & RM=Atwell Branch,Main      ,237.6
675.9318
Boundary for River Rch & Prof#=Atwell Branch,Main      ,1
Up Type=0
Dn Type=3
Dn Slope=0.039182

--- Atwell Branch.g01 (geometry) ---

Geom Title=Geometry
Program Version=4.00

River Reach=Atwell Branch   ,Main
Reach XY= 30
     1747616.805      129763.636     1747643.349      129639.593
     1747625.976      129584.801     1747606.746      129562.519
     1747590.496      129528.758      1747592.64      129432.284
     1747601.921      129406.395     1747599.248       129356.28
     1747581.207      129272.756     1747534.664      129178.036
     1747516.038       129071.43     1747484.167        128986.8
     1747401.957      128829.591     1747333.308      128718.826
     1747276.512      128657.352     1747147.551      128388.739
     1747093.287      128311.538     1747019.927       128266.46
     1746977.205      128231.328     1746956.367      128203.544
     1746936.686      128150.291     1746937.366       128104.43
      1746926.38      128028.584     1746866.911      127977.133
     1746829.492      127960.429     1746775.369      127922.342
     1746702.335      127859.203     1746680.593      127750.535
     1746661.776      127713.866     1746616.684      127665.054

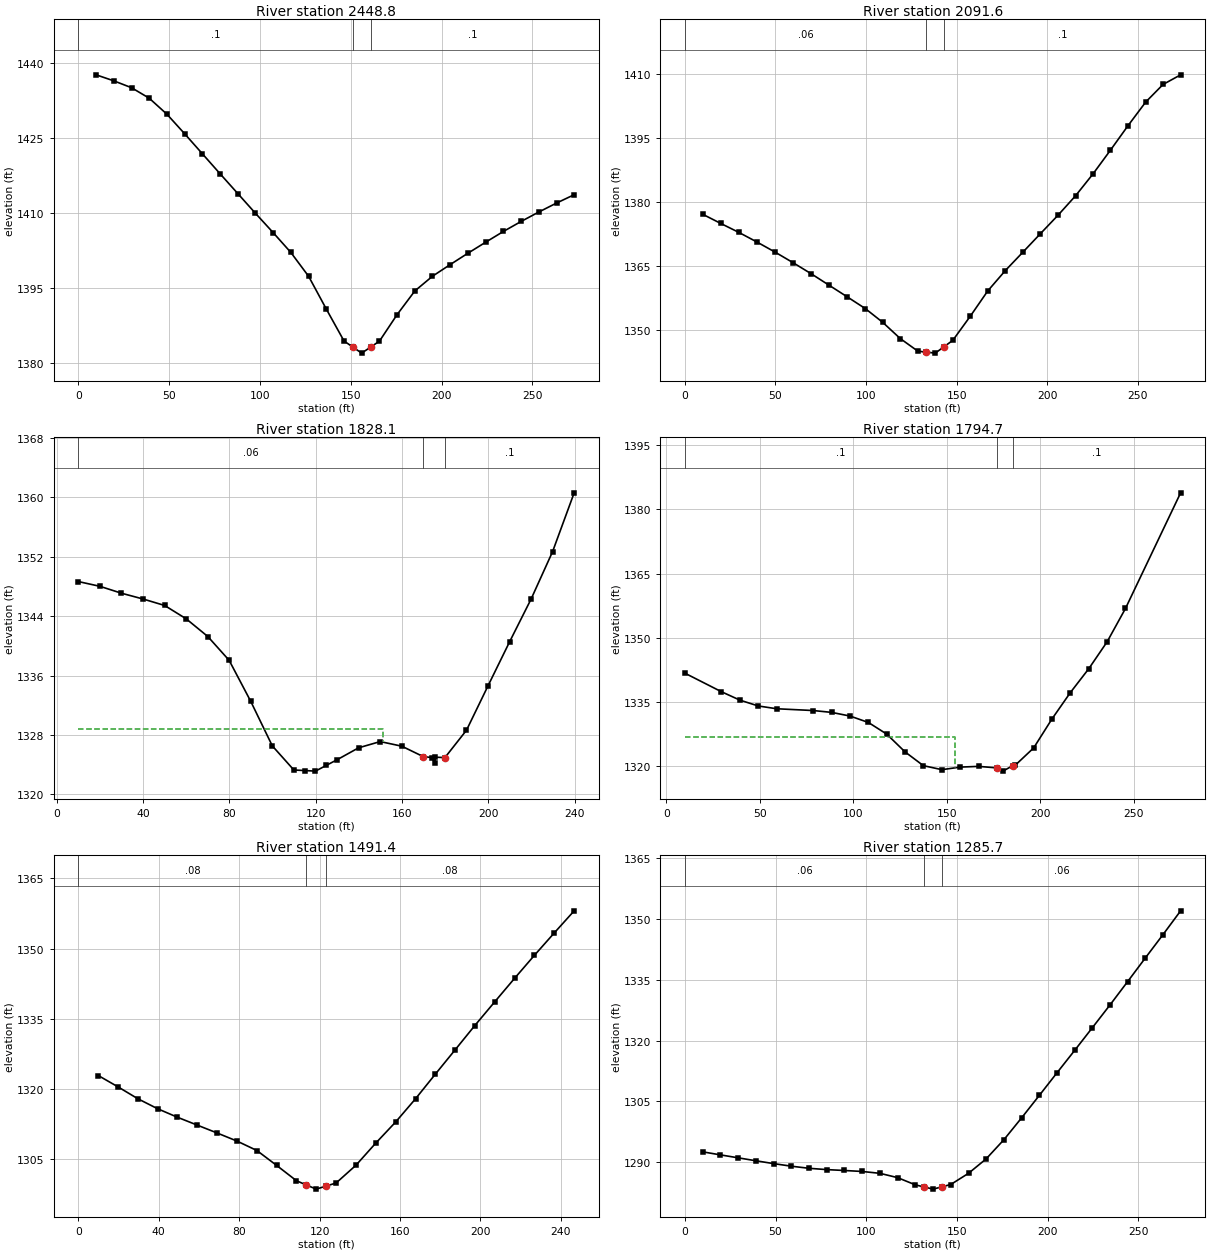
Type RM Length L Ch R = 1 ,2448.8  ,357.6,357.2,356.7
XS GIS Cut Line= 3
     1747776.371      129756.693     1747639.873      129755.951
     1747503.375      129755.209
#Sta/Elev= 30
     9.8 1437.71    19.5 1436.51    29.3 1435.13      39 1433.04    48.8 1429.82
    58.5 1425.93    68.3 1421.91      78 1417.93    87.8 1413.95    97.5 1410.01
   107.3 1406.12     117 1402.17   126.8 1397.39   136.5 1390.86   146.3 1384.44
     151 1383.27     156 1382.02     161 1383.24   165.8 1384.42   175.5 1389.72
   185.3 1394.47     195 1397.41   204.8 1399.75   214.5 1402.01   224.3 1404.22
     234 1406.36   243.8 1408.37   253.5 1410.25   263.3 1412.05     273 1413.72
#Mann= 3 , 0 , 0
       0      .1       0     151    .045       0     161      .1       0
Bank Sta=151,161
XS Rating Curve= 0 ,0
Exp/Cntr=0.3,0.1

Type RM Length L Ch R = 1 ,2091.6  ,269.5,263.5,257.5
XS GIS Cut Line= 3
     1747736.017      129411.093     1747636.576      129415.818
     1747462.539      129416.442
#Sta/Elev= 30
      10 1377.13    19.9 1374.99    29.9 1372.88    39.8 1370.64    49.8 1368.27
    59.7 1365.79    69.7 1363.19    79.6 1360.49    89.6 1357.76    99.6    1355
   109.2 1351.77   118.9 1347.95   128.6 1344.99   133.2 1344.77   138.2 1344.53
   143.2 1346.08   147.9 1347.54   157.6 1353.24   167.2 1359.16   176.9 1363.94
   186.6 1368.27   196.2 1372.58   205.9 1376.91   215.6 1381.49   225.2 1386.61
   234.9 1392.23   244.6 1397.99   254.3 1403.51   263.9 1407.66   273.6 1409.92
#Mann= 3 , 0 , 0
       0     .06       0   133.2    .045       0   143.2      .1       0
Bank Sta=133.2,143.2
XS Rating Curve= 0 ,0
Exp/Cntr=0.3,0.1

Type RM Length L Ch R = 1 ,1828.1  ,36.6,33.5,30.4
XS GIS Cut Line= 2
     1747700.724      129112.024     1747472.345      129185.278
#Sta/Elev= 29
      10 1348.67      20 1348.03      30  1347.1      40 1346.32      50 1345.45
      60 1343.65      70 1341.27    79.9 1338.06    89.9 1332.54    99.9 1326.54
   109.9 1323.29   114.9 1323.22   119.9 1323.14   124.9 1323.91   129.9 1324.67
   139.9 1326.28   149.9 1327.12   159.9  1326.5   169.9 1325.09  173.78 1324.97
   175.3 1324.27   175.4 1325.02   179.9 1324.96   189.9 1328.65   199.9 1334.64
   209.9 1340.57   219.9 1346.35   229.8  1352.7   239.8 1360.62
#Mann= 3 , 0 , 0
      10     .06       0   169.9    .045       0   179.9      .1       0
#XS Ineff= 2 , 0
          151.01  1328.8
Permanent Ineff=
       F       F
Bank Sta=169.9,179.9
XS Rating Curve= 0 ,0
Exp/Cntr=0.3,0.1

Type RM Length L Ch R = 1 ,1794.7  ,304.6,303.2,301.7
XS GIS Cut Line= 3
     1747689.482      129055.007     1747582.711      129104.755
     1747441.726      129174.254
#Sta/Elev= 26
     9.8 1341.72    29.4 1337.37    39.3  1335.4    49.1 1334.04    58.9 1333.39
    78.5 1332.97    88.3 1332.54    98.2 1331.68     108 1330.18   117.8 1327.46
   127.6  1323.3   137.4 1320.08   147.3 1319.14   157.1 1319.74   166.9 1319.91
   176.7 1319.56  179.94  1318.8  185.12 1320.05   186.6  1320.2   196.4 1324.23
   206.2 1331.01     216 1337.16   225.9 1342.77   235.7 1349.06   245.5 1356.84
     275 1383.89
#Mann= 3 , 0 , 0
     9.8      .1       0   176.7    .045       0  185.12      .1       0
#XS Ineff= 2 , 0
          154.14 1326.69
Permanent Ineff=
       F       F
Bank Sta=176.7,185.12
XS Rating Curve= 0 ,0
Exp/Cntr=0.3,0.1

Type RM Length L Ch R = 1 ,1491.4  ,208.6,205.7,201.5
XS GIS Cut Line= 2
     1747518.179      128793.338      1747305.71      128918.437
#Sta/Elev= 27
     9.9 1322.86    19.7 1320.44    29.6 1317.89    39.4 1315.76    49.3 1313.93
    59.2 1312.24      69 1310.57    78.9 1308.84    88.8 1306.82    98.6 1303.64
   108.5 1300.35   113.4 1299.45   118.3 1298.56   123.4 1299.24   128.2 1299.87
   138.1 1303.68   147.9 1308.39   157.8 1312.91   167.7 1317.88   177.5 1323.12
   187.4 1328.35   197.2 1333.55   207.1 1338.62     217 1343.66   226.8 1348.55
   236.7 1353.35   246.6 1358.08
#Mann= 3 , 0 , 0
       0     .08       0   113.4    .045       0   123.4     .08       0
Bank Sta=113.4,123.4
XS Rating Curve= 0 ,0
Exp/Cntr=0.3,0.1

Type RM Length L Ch R = 1 ,1285.7  ,294.6,295.2,297.2
XS GIS Cut Line= 3
     1747407.747      128598.249     1747300.979      128683.938
     1747200.772       128776.52
#Sta/Elev= 30
     9.8 1292.58    19.6 1291.83    29.3 1291.11    39.1 1290.38    48.9 1289.68
    58.7 1289.04    68.5 1288.52    78.2  1288.2      88 1287.98    97.8 1287.74
   107.6 1287.28   117.3 1286.22   127.1 1284.44   131.9 1283.92   136.9 1283.39
   141.9 1283.98   146.6 1284.53   156.4 1287.29   166.1 1290.84   175.9 1295.57
   185.6 1300.92   195.4 1306.47   205.1 1312.02   214.9 1317.57   224.6 1323.13
   234.4 1328.78   244.1 1334.52   253.8 1340.31   263.6  1346.1   273.3 1351.95
#Mann= 3 , 0 , 0
       0     .06       0   131.9    .045       0   141.9     .06       0
Bank Sta=131.9,141.9
XS Rating Curve= 0 ,0
Exp/Cntr=0.3,0.1

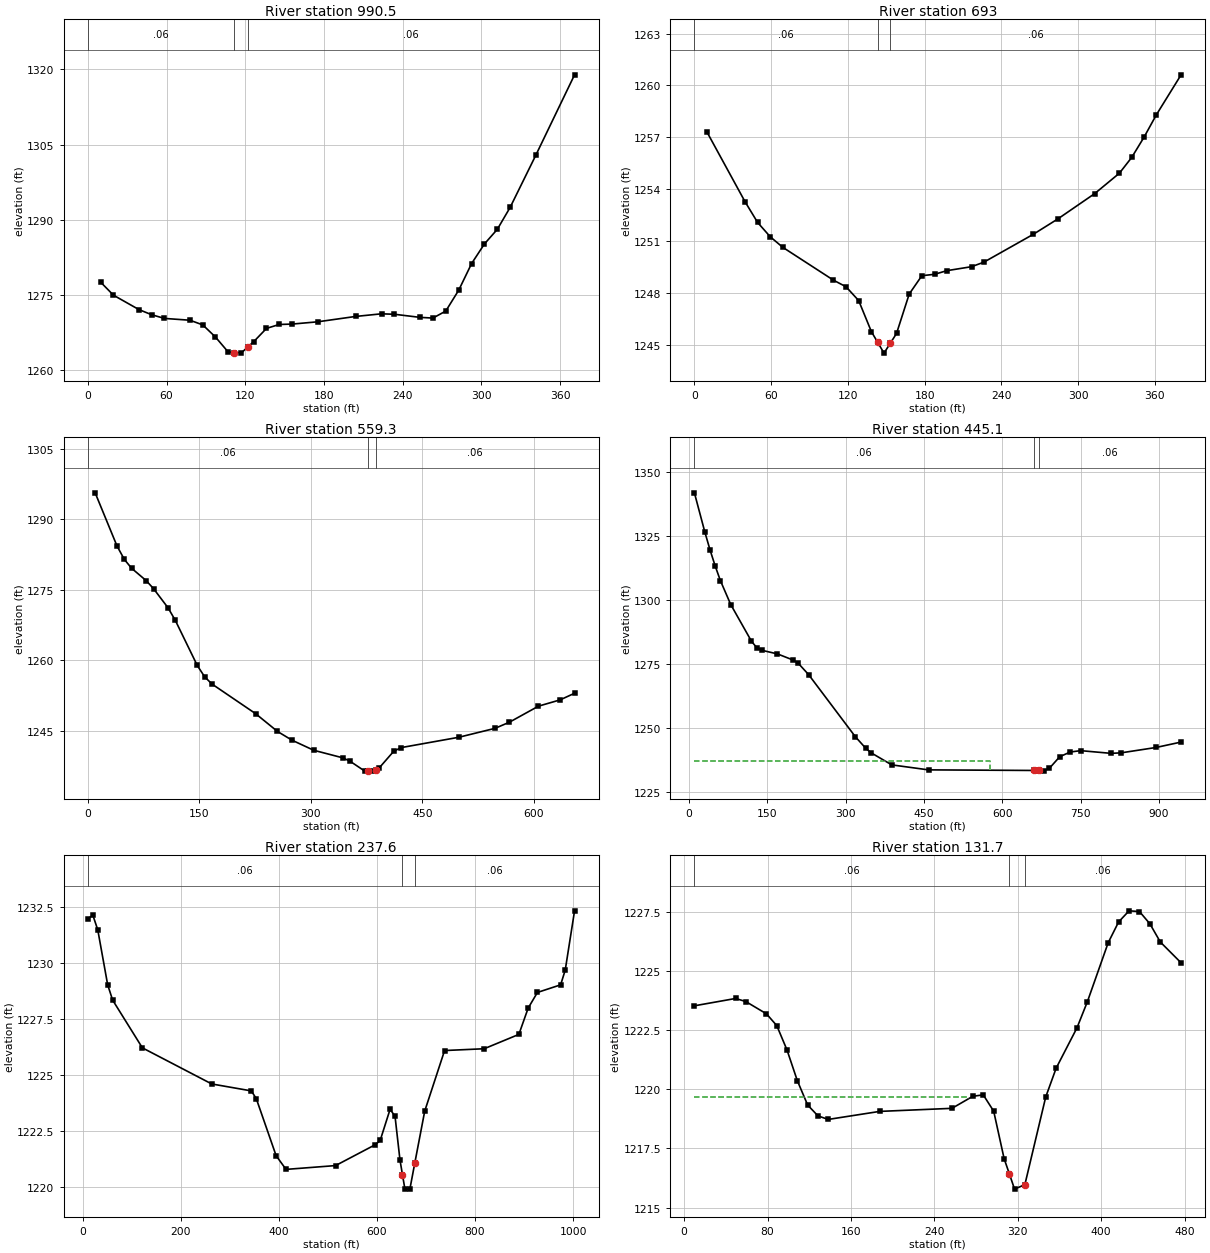
Type RM Length L Ch R = 1 ,990.5   ,295,297.4,299.9
XS GIS Cut Line= 3
     1747254.082      128356.485     1747083.312      128485.555
      1747047.57      128638.454
#Sta/Elev= 30
     9.7 1277.53    19.5 1274.92    38.9 1272.05    48.6 1271.02    58.4 1270.28
    77.8 1269.92    87.6 1268.99    97.3 1266.56     107 1263.57   111.8 1263.47
   116.8 1263.35   121.8 1264.54   126.5 1265.65   136.2 1268.29   145.9 1269.07
   155.7 1269.15   175.1  1269.6   204.3 1270.68   223.9  1271.2   233.7 1271.11
   253.3 1270.49   263.1 1270.35   272.9 1271.75   282.8 1275.93   292.6 1281.24
   302.4 1285.16   312.2 1288.07     322 1292.46   341.6 1302.89   371.1 1318.92
#Mann= 3 , 0 , 0
       0     .06       0   111.8    .045       0   121.8     .06       0
Bank Sta=111.8,121.8
XS Rating Curve= 0 ,0
Exp/Cntr=0.3,0.1

Type RM Length L Ch R = 1 ,693     ,132.5,133.7,134.9
XS GIS Cut Line= 3
     1747091.255      128140.045     1746928.428      128233.372
     1746843.043      128406.128
#Sta/Elev= 27
     9.9 1257.29    39.5 1253.28    49.4 1252.07    59.3 1251.24    69.1 1250.63
   108.7 1248.73   118.5 1248.35   128.4 1247.55   138.3 1245.76   143.2 1245.14
   148.2 1244.51   153.2 1245.09     158 1245.65   167.9 1247.93   177.8 1248.99
   187.7 1249.07   197.3 1249.28   216.6 1249.51   226.2 1249.77   264.8 1251.38
     284 1252.27   312.9 1253.74   332.2 1254.92   341.8 1255.83   351.5 1257.01
   361.1  1258.3   380.4 1260.61
#Mann= 3 , 0 , 0
       0     .06       0   143.2    .045       0   153.2     .06       0
Bank Sta=143.2,153.2
XS Rating Curve= 0 ,0
Exp/Cntr=0.3,0.1

Type RM Length L Ch R = 1 ,559.3   ,122.5,114.2,105.9
XS GIS Cut Line= 4
     1747301.739      128008.989      1747047.57      128030.831
     1746880.771      128112.245     1746811.272      128314.786
#Sta/Elev= 30
     9.8 1295.63    39.2 1284.31    49.1 1281.44    58.9 1279.56    78.5 1276.93
    88.3 1275.24   107.9 1271.14   117.7 1268.46   147.2 1258.87     157 1256.49
   166.8 1254.94   225.7 1248.61   255.1 1244.83   274.6 1242.97   303.9 1240.82
     343 1239.21   352.8 1238.48   372.3 1236.41   377.1  1236.4   382.1 1236.38
   387.1 1236.72   391.9 1237.05   411.4 1240.59   421.2 1241.38   499.1 1243.59
   547.8 1245.49   567.2  1246.8   606.2 1250.21   635.4 1251.55   654.8 1252.96
#Mann= 3 , 0 , 0
       0     .06       0   377.1    .045       0   387.1     .06       0
Bank Sta=377.1,387.1
XS Rating Curve= 0 ,0
Exp/Cntr=0.3,0.1

Type RM Length L Ch R = 1 ,445.1   ,208.1,207.5,207
XS GIS Cut Line= 4
     1747452.116      127780.708     1747063.972      127777.822
     1746824.515      128062.721     1746773.867      128237.819
#Sta/Elev= 30
      10 1341.99    29.9 1326.73    39.8 1319.78    49.8 1313.42    59.7 1307.73
    79.6 1298.35   119.4 1283.98   129.4  1281.5   139.3 1280.46   169.2 1279.04
   199.1 1276.65     209 1275.39   228.9 1270.94   318.5 1246.66   338.4 1242.16
   348.3 1240.44   388.2 1235.68   458.6 1233.73     660  1233.5  665.72 1233.24
     6701233.499   679.9 1233.47   689.9 1234.27     710 1238.86   730.1 1240.71
   750.3 1241.24   808.3 1240.19   827.5 1240.38   894.6 1242.48   942.6  1244.6
#Mann= 3 , 0 , 0
      10     .06       0     660    .045       0     670     .06       0
#XS Ineff= 2 , 0
          576.86  1237.1
Permanent Ineff=
       F       F
Bank Sta=660,670
XS Rating Curve= 0 ,0
Exp/Cntr=0.3,0.1

Type RM Length L Ch R = 1 ,237.6   ,109.8,105.9,102.1
XS GIS Cut Line= 3
     1747121.688      127363.706     1746566.929       128058.98
     1746556.489      128172.079
#Sta/Elev= 30
    10.1 1231.97    20.2 1232.14    30.3 1231.48    50.5 1229.03    60.6 1228.35
   121.3 1226.22   262.8 1224.61   343.7  1224.3   353.8 1223.95   394.2 1221.41
   414.4  1220.8   515.5 1220.97   596.4  1221.9   606.5 1222.09   626.7 1223.48
   636.8 1223.17   646.9 1221.22     652 1220.56     657 1219.92   667.1 1219.92
   677.2 1221.09   697.4  1223.4   737.9  1226.1   818.7 1226.18   889.5 1226.82
   908.4 1227.99   927.3 1228.69   974.7 1229.03   984.1 1229.69  1003.1 1232.33
#Mann= 3 , 0 , 0
    10.1     .06       0     652    .045       0   677.2     .06       0
#XS Ineff= 2 , 0
          620.98 1223.07
Permanent Ineff=
       F       F
Bank Sta=652,677.2
XS Rating Curve= 0 ,0
Exp/Cntr=0.3,0.1

Type RM Length L Ch R = 1 ,131.7   ,123.5,131.7,139.8
XS GIS Cut Line= 3
      1746882.42      127537.447     1746727.873      127717.092
     1746582.872      127907.903
#Sta/Elev= 30
     9.9 1223.54    49.4 1223.85    59.2 1223.72      79  1223.2    88.9  1222.7
    98.7 1221.67   108.6 1220.37   118.5 1219.34   128.4 1218.88   138.2 1218.73
   187.6 1219.07   256.9  1219.2   276.9 1219.71   286.9 1219.77   296.9 1219.08
   306.9 1217.07   311.9 1216.43   316.9 1215.78   326.8 1215.97   346.8 1219.68
   356.8  1220.9   376.8 1222.61   386.8 1223.72   406.7 1226.21   416.7 1227.09
   426.7 1227.56   436.7 1227.53   446.7 1227.01   456.7 1226.24   476.6 1225.36
#Mann= 3 , 0 , 0
     9.9     .06       0   311.9    .045       0   326.8     .06       0
#XS Ineff= 2 , 0
          271.81 1219.68
Permanent Ineff=
       F       F
Bank Sta=311.9,326.8
XS Rating Curve= 0 ,0
Exp/Cntr=0.3,0.1
Stream Node=Atwell Branch   ,Main            , 0 , 0 ,Upstream end
Stream Node=Atwell Branch   ,Main            , 0 , 1 ,Downstream end

Chan Stop Cuts=-1
Use User Specified Reach Order=0